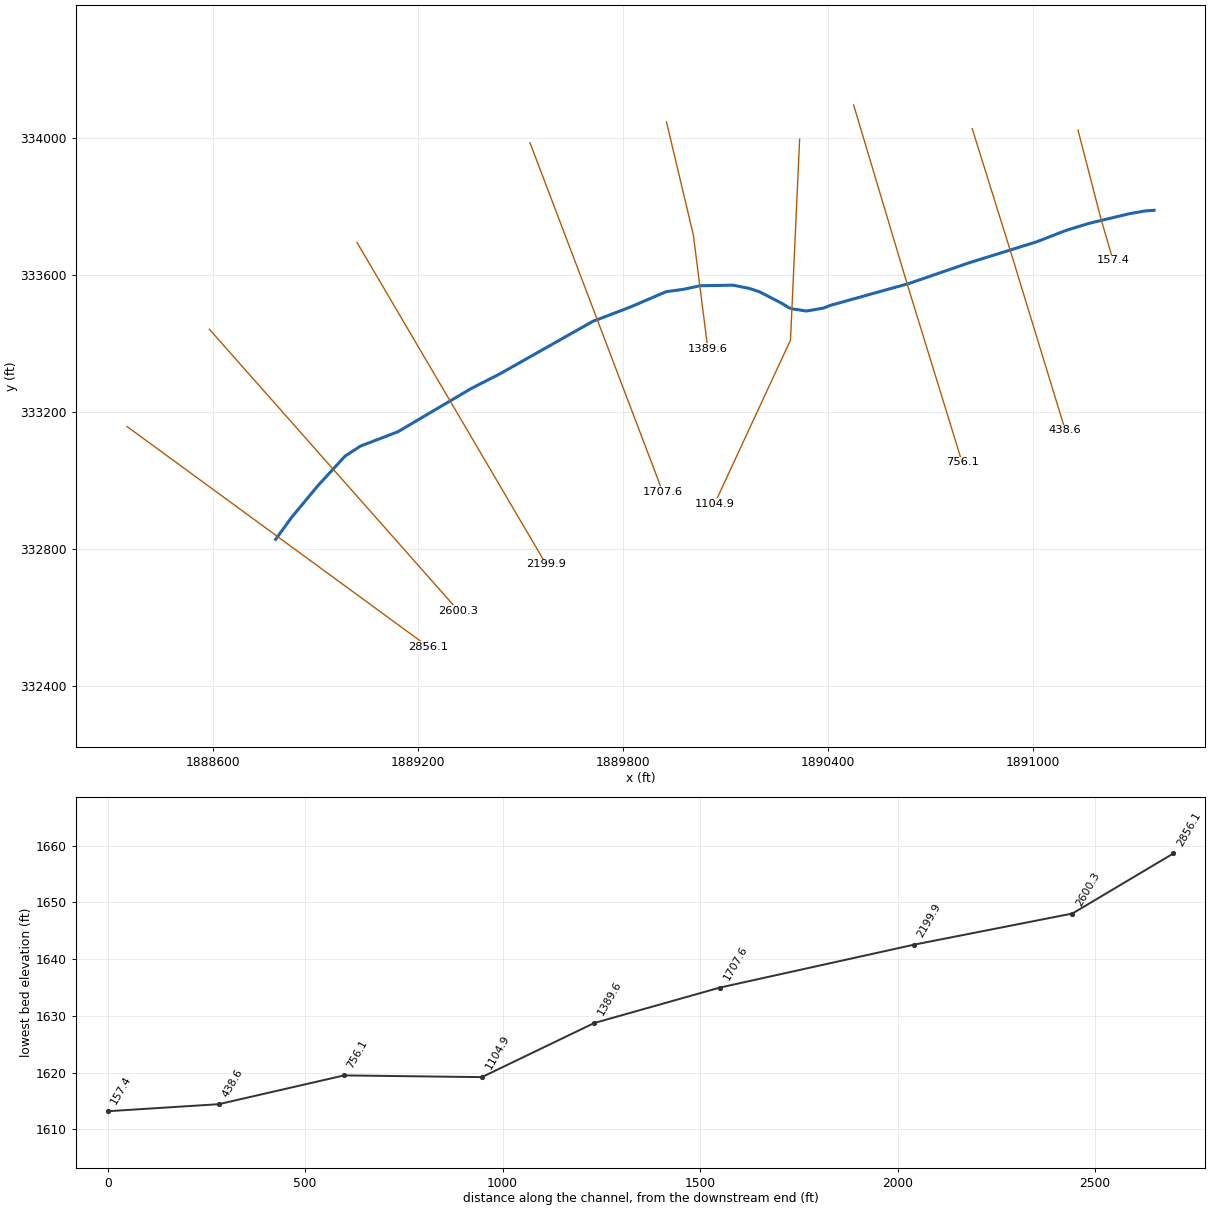
--- WillisBrch.prj (project) ---

Proj Title=WillisBrch
Current Plan=p01
Default Exp/Contr=0,0
English Units
Geom File=g01
Flow File=f01
Plan File=p01
BEGIN DESCRIPTION:
END DESCRIPTION:
DSS Export Rating Curves= 0
DSS Export Rating Curve Sorted= 0
DSS Export Volume Flow Curves= 0
DXF OffsetX= 0
DXF OffsetY= 0
DXF ScaleX= 0
DXF ScaleY= 0

--- WillisBrch.p01 (plan) ---

Plan Title=Floodplain
Program Version=4.00
Geom File=g01
Flow File=f01
K Sum by GR=0
Std Step Tol=0.01
Critical Tol=0.01
Num of Std Step Trials=20
Max Error Tol=0.3
Flow Tol Ratio=0.001
Split Flow NTrial=30
Split Flow Tol=0.02
Split Flow Ratio=0.02
Log Output Level=0
Friction Slope Method=1
Unsteady Friction Slope Method=2
Unsteady Bridges Friction Slope Method=1
Global Log Level=0
CheckData=False
Run HTab=0
Run UNet=0
Run PostProcess=0
UNET Theta=0
UNET Theta Warmup=0
UNET ZTol=0
UNET ZSATol=0
UNET MxIter=0
UNET MaxInSteps=0
UNET DtIC=0
UNET DtMin=0
UNET MaxCRTS=0
UNET WFStab=0
UNET SFStab=0
UNET WFX=0
UNET SFX=0
UNET DSS MLevel=0
UNET DZMax Abort=0
UNET Convert EG Bridges=0
UNET Use Existing IB Tables=0
UNET Froude Limit=0
UNET Froude Power=0
Write IC File=0
Echo Input=False
Echo Output=False
Write Detailed=0

--- WillisBrch.f01 (steady flow) ---

Flow Title=NFF Regression Equation
Program Version=4.00
Number of Profiles=1
Profile Names=P100yr
River Rch & RM=WillisBrch,Main      ,2856.1
821.5581
River Rch & RM=WillisBrch,Main      ,2600.3
909.5346
River Rch & RM=WillisBrch,Main      ,157.4
970.7408
Boundary for River Rch & Prof#=WillisBrch,Main      ,1
Up Type=0
Dn Type=3
Dn Slope=0.00658

--- WillisBrch.g01 (geometry) ---

Geom Title=USGS 3m DEM
Program Version=4.10

River Reach=WillisBrch      ,Main
Reach XY= 30
     1888782.642      332827.201     1888829.517      332891.437
     1888905.906      332983.451     1888985.767      333070.257
     1889030.906      333099.771     1889140.281      333141.437
     1889355.559      333268.173     1889440.629      333311.576
     1889711.462      333464.354     1889820.837      333506.021
     1889926.739      333551.159     1889977.087      333558.104
     1890025.698      333568.521     1890122.052      333570.257
     1890167.981      333561.295     1890199.309      333551.159
     1890263.545      333518.173     1890286.114      333504.284
     1890294.205      333501.304     1890337.254      333494.681
     1890387.245      333503.216     1890407.642      333511.229
     1890638.545      333575.465     1890815.628      333636.229
     1891011.809      333696.993     1891096.878      333729.979
     1891164.587      333750.812     1891280.906       333778.59
     1891329.517       333787.27     1891355.559      333789.007

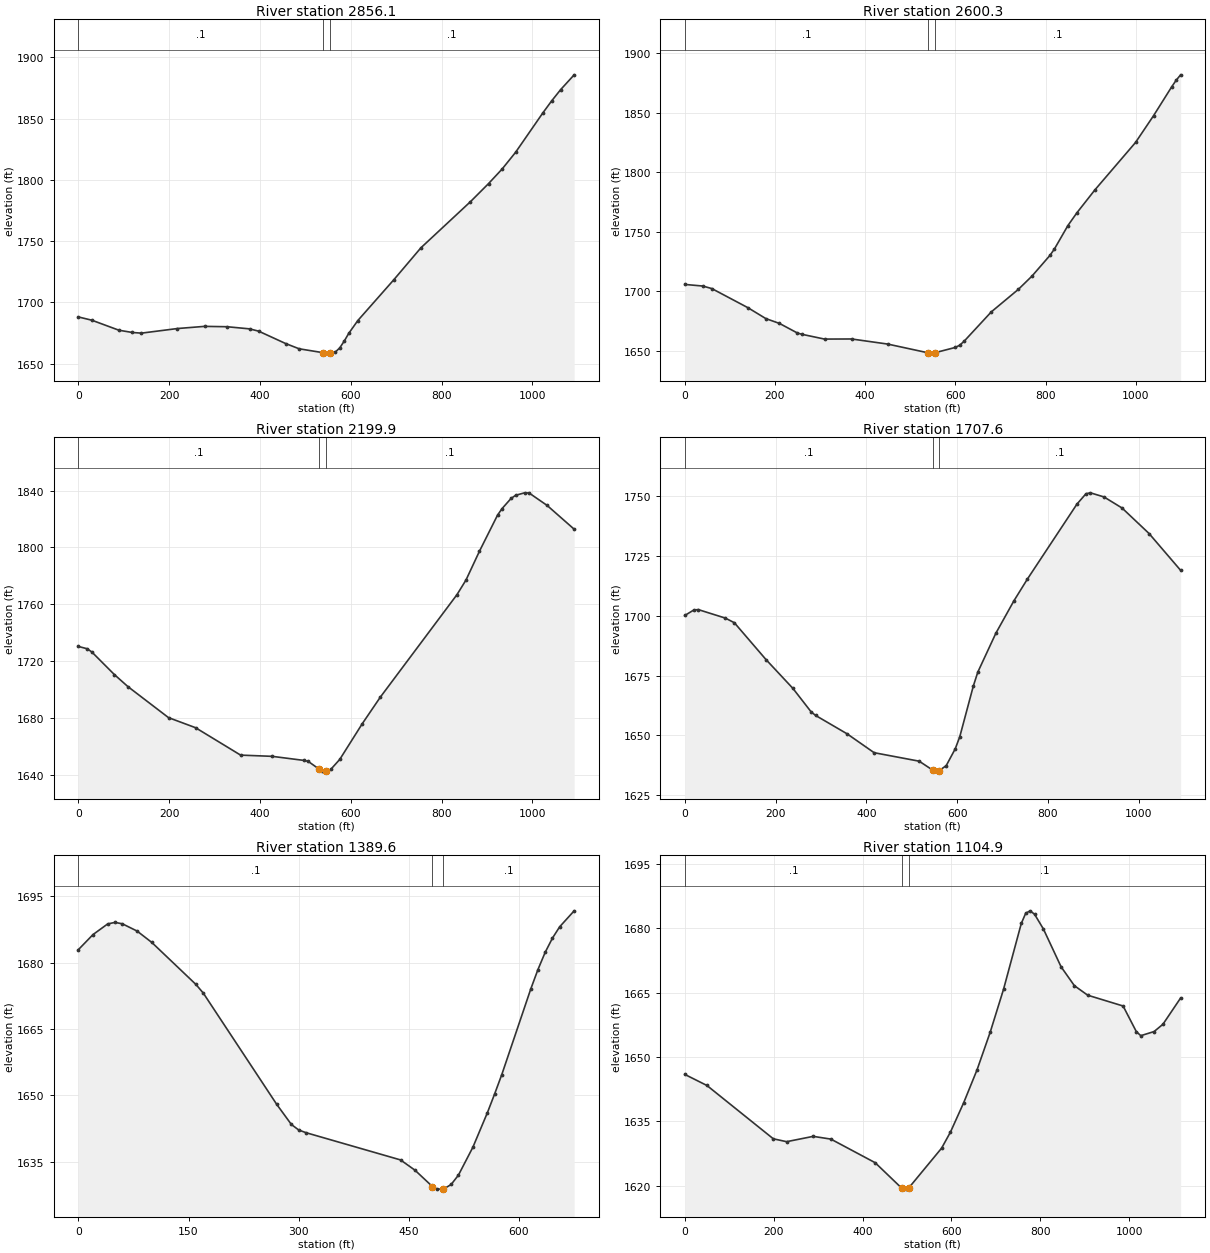
Type RM Length L Ch R = 1 ,2856.1  ,260.7,255.8,251
XS GIS Cut Line= 3
     1888347.483      333157.129     1888788.537      332835.279
     1889229.591      332513.429
#Sta/Elev= 30
       0 1688.16    29.8 1685.48    89.4 1677.32   119.1 1675.47     139 1674.94
   218.4  1678.7     278 1680.46   327.6 1680.17   377.2 1678.42   397.1 1676.56
   456.6 1666.45   486.4 1662.16   538.5 1659.02   553.5 1658.64   555.9 1658.63
   565.8 1659.43   575.8 1662.93   585.7 1668.51   595.6 1674.77   615.5 1685.19
   694.9 1718.53   754.5 1744.57   863.7 1782.22   903.4 1796.93   933.2 1808.77
     963 1822.47  1022.5 1854.34  1042.4  1864.4  1062.2  1873.6    1092 1885.69
#Mann= 3 , 0 , 0
       0      .1       0   538.5    .045       0   553.5      .1       0
Bank Sta=538.5,553.5
XS Rating Curve= 0 ,0
Exp/Cntr=0.3,0.1

Type RM Length L Ch R = 1 ,2600.3  ,404.8,400.4,396
XS GIS Cut Line= 2
     1888588.646      333441.389     1889317.903      332618.725
#Sta/Elev= 30
       0 1705.76      40  1704.4      60 1702.26   139.9 1686.22   179.9 1677.01
   209.9    1673   249.8 1664.92   259.8 1663.85   309.8 1659.84   369.8 1659.93
   449.7 1655.66   538.9 1648.34   549.7 1648.04   553.9  1648.3   599.6  1652.8
   609.6 1654.69   619.6 1658.13   679.6 1682.69   739.6 1701.61   769.6 1712.68
   809.5 1730.08   819.5  1735.5   849.5 1755.24   869.5 1765.99   909.5 1785.27
   999.4 1825.02  1039.4 1847.54  1079.4 1871.66  1089.4 1877.26  1099.4 1881.86
#Mann= 3 , 0 , 0
       0      .1       0   538.9    .045       0   553.9      .1       0
Bank Sta=538.9,553.9
XS Rating Curve= 0 ,0
Exp/Cntr=0.3,0.1

Type RM Length L Ch R = 1 ,2199.9  ,496.1,492.3,488.5
XS GIS Cut Line= 3
     1889021.171      333694.942      1889298.17      333224.424
     1889575.169      332753.906
#Sta/Elev= 30
       0 1730.34    19.8 1728.67    29.8  1726.4    79.4 1710.52   109.2 1702.05
   198.6 1680.22   258.1 1673.14   357.4 1653.83   426.9 1652.97   496.4 1650.12
   506.3 1649.42   529.9 1644.05   536.1 1642.77   544.9 1642.58     546 1642.56
   555.9 1643.76   575.8 1650.83   625.4 1675.97   665.1 1694.64   833.9 1766.78
   853.8 1777.09   883.5 1797.41   923.2 1822.72   933.2 1827.36     953  1834.5
     963 1836.72   982.8 1838.46   992.7 1838.35  1032.4  1829.6    1092 1812.86
#Mann= 3 , 0 , 0
       0      .1       0   529.9    .045       0   544.9      .1       0
Bank Sta=529.9,544.9
XS Rating Curve= 0 ,0
Exp/Cntr=0.3,0.1

Type RM Length L Ch R = 1 ,1707.6  ,323.2,317.9,312.5
XS GIS Cut Line= 3
     1889527.773      333986.348     1889722.147      333476.118
     1889916.522      332965.888
#Sta/Elev= 30
       0 1700.12    19.8  1702.4    29.8 1702.57    89.4 1699.01   109.2 1697.07
   178.7 1681.69   238.2 1669.58     278 1659.84   287.9 1658.31   357.4  1650.6
     417  1642.7   516.2 1639.15   545.7 1635.45   555.9 1634.99   560.7 1635.24
   575.8 1637.31   595.6 1644.32   605.6 1649.38   635.4 1670.56   645.3 1676.41
     685 1692.66   724.7  1706.2   754.5 1715.34   863.7 1746.72   883.5 1751.04
   893.4 1751.43   923.2 1749.71     963 1745.08  1022.5  1734.4    1092    1719
#Mann= 3 , 0 , 0
       0      .1       0   545.7    .045       0   560.7      .1       0
Bank Sta=545.7,560.7
XS Rating Curve= 0 ,0
Exp/Cntr=0.3,0.1

Type RM Length L Ch R = 1 ,1389.6  ,287.8,284.5,280.7
XS GIS Cut Line= 3
     1889927.436      334047.509     1890006.284      333716.628
     1890048.524      333384.339
#Sta/Elev= 30
       0 1682.94      20 1686.37      40 1688.78      50 1689.12      60  1688.8
      80 1687.16     100 1684.59   160.1 1675.08   170.1 1673.13   270.1 1647.94
   290.1 1643.38   300.1 1642.13   310.1 1641.52   438.7 1635.36   458.4 1633.03
   482.1 1629.34   487.9 1628.75   497.1 1628.75   507.6  1629.8   517.5 1631.91
   537.2 1638.23   556.9 1646.02   566.7 1650.24   576.6 1654.69     616 1674.04
   625.8 1678.45   635.7 1682.37   645.6 1685.58   655.4 1688.13   675.1 1691.74
#Mann= 3 , 0 , 0
       0      .1       0   482.1    .045       0   497.1      .1       0
Bank Sta=482.1,497.1
XS Rating Curve= 0 ,0
Exp/Cntr=0.3,0.1

Type RM Length L Ch R = 1 ,1104.9  ,341.8,348.9,356.7
XS GIS Cut Line= 3
     1890317.453      333996.821     1890290.701      333409.683
     1890068.237      332930.961
#Sta/Elev= 30
       0 1645.94    49.8 1643.36   199.2 1630.94   229.1 1630.27   288.9 1631.51
   328.7 1630.87   428.4 1625.37   488.6 1619.39   498.1 1619.22   503.6 1619.46
   577.8 1628.76   597.7  1632.5   627.6 1639.37   657.5 1646.99   687.4 1655.85
   717.2 1665.78   757.1  1681.1     767 1683.47     777 1684.04     787 1683.24
   806.9  1679.8   846.7 1670.99   876.6  1666.6   906.5 1664.39   986.2 1661.87
    1016 1655.89    1026 1654.96  1055.9 1655.92  1075.8 1657.62  1115.6 1663.74
#Mann= 3 , 0 , 0
       0      .1       0   488.6    .045       0   503.6      .1       0
Bank Sta=488.6,503.6
XS Rating Curve= 0 ,0
Exp/Cntr=0.3,0.1

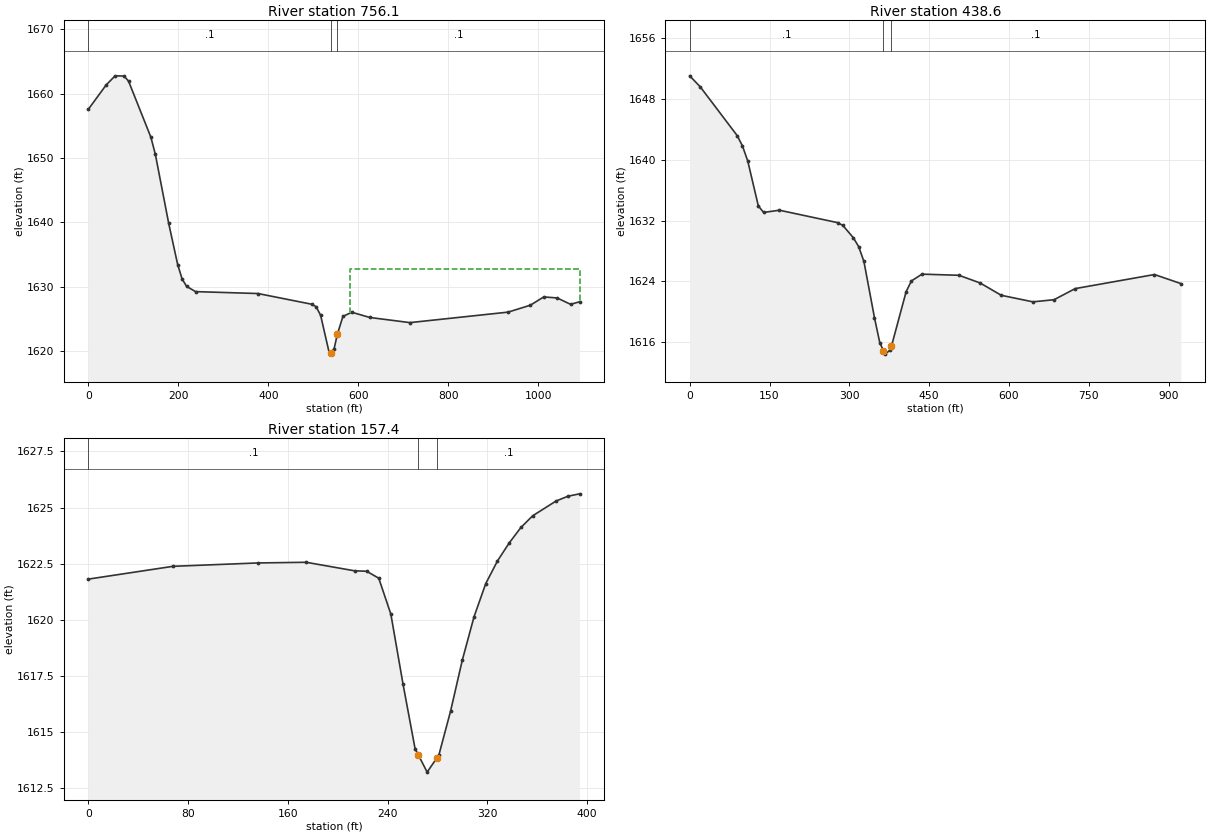
Type RM Length L Ch R = 1 ,756.1   ,317.2,317.4,317.4
XS GIS Cut Line= 3
     1890475.621      334096.919     1890632.463      333573.773
     1890793.408      333052.172
#Sta/Elev= 30
       0 1657.59    39.7 1661.38    59.6 1662.79    79.4 1662.76    89.4 1661.96
     139 1653.25     149 1650.57   178.7 1639.83   198.6 1633.44   208.5  1631.2
   218.5 1630.05   238.3 1629.24   377.3 1628.94   496.5 1627.28   506.4 1626.89
   516.4 1625.56   536.2 1619.52   538.7 1619.72   546.2  1620.3   553.7 1622.63
     566 1625.39   585.8 1626.03   625.6 1625.22   714.9 1624.42   933.2 1626.05
   982.8 1627.13  1012.6 1628.42  1042.4 1628.25  1072.2 1627.26    1092 1627.66
#Mann= 3 , 0 , 0
       0      .1       0   538.7    .045       0   553.7      .1       0
#XS Ineff= 2 , 0
                          582.78         1632.83
Permanent Ineff=
       F       F
Bank Sta=538.7,553.7
XS Rating Curve= 0 ,0
Exp/Cntr=0.3,0.1

Type RM Length L Ch R = 1 ,438.6   ,282.2,281.2,280.9
XS GIS Cut Line= 3
     1890822.927      334027.797     1890935.545      333668.012
     1891095.524      333145.975
#Sta/Elev= 30
       0 1651.02    19.8 1649.58    89.3 1643.16    99.2  1641.8   109.1 1639.83
     129 1633.92   138.9 1633.07   168.7 1633.36   277.8 1631.73   287.7 1631.37
   307.6 1629.74   317.5 1628.58   327.4 1626.63   347.2 1619.25   357.2 1615.96
   364.1 1614.91   367.1 1614.45     377    1615   379.1 1615.48   406.8 1622.67
   416.7 1624.07   436.6 1624.96     506 1624.81   545.8  1623.8   585.5 1622.18
     645 1621.32   684.7  1621.6   724.4 1623.06   873.4 1624.91     923 1623.72
#Mann= 3 , 0 , 0
       0      .1       0   364.1    .045       0   379.1      .1       0
Bank Sta=364.1,379.1
XS Rating Curve= 0 ,0
Exp/Cntr=0.3,0.1

Type RM Length L Ch R = 1 ,157.4   ,161.6,157.4,152.4
XS GIS Cut Line= 3
     1891132.689      334023.573      1891200.95       333760.56
     1891235.473      333643.412
#Sta/Elev= 25
       0 1621.81    67.9 1622.38   135.9 1622.53   174.7 1622.56   213.5 1622.18
   223.2 1622.16   232.9 1621.85   242.6 1620.25   252.3 1617.15     262 1614.26
   264.6 1613.98   271.7 1613.21   279.6 1613.85   281.1 1613.97   290.5 1615.93
   299.9  1618.2   309.3 1620.13   318.7 1621.61   328.1 1622.62   337.5 1623.42
   346.9 1624.11   356.3 1624.63   375.1 1625.29   384.5  1625.5   393.9 1625.61
#Mann= 3 , 0 , 0
       0      .1       0   264.6    .045       0   279.6      .1       0
Bank Sta=264.6,279.6
XS Rating Curve= 0 ,0
Exp/Cntr=0.3,0.1

Chan Stop Cuts=-1
Use User Specified Reach Order=0
Composite Channel Slope=5